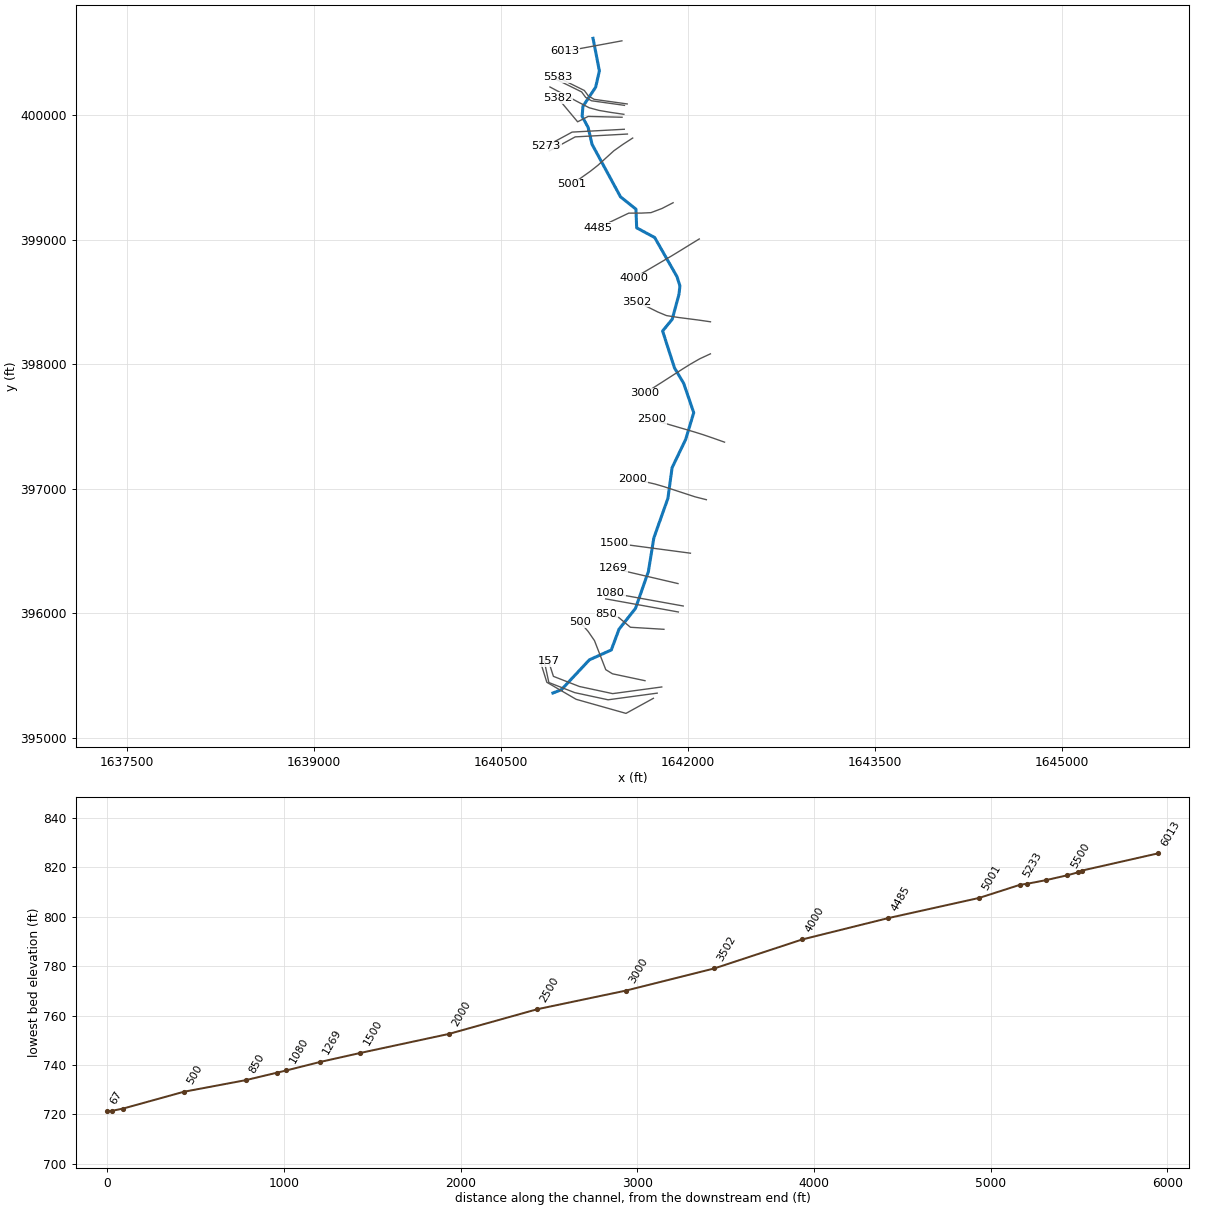
--- BARKERRN.prj (project) ---

Proj Title=BARKERRN
Current Plan=p01
Default Exp/Contr=0,0
English Units
Geom File=g01
Flow File=f01
Plan File=p01
BEGIN DESCRIPTION:
---------- MODELED AS PART OF WVEMD CTP PROGRAM, 2023----------
Stream Name: Barker Run
Flood Zone:  AFH
Wetzel County, WV
HEC-RAS Version: RAS 6.3
Vertical Datum: NAVD88
Projection: NAD 1983 StatePlane West Virginia S FIPS 4702 (US Feet)
Terrain: 1-meter West Virginia FEMA R3 South Central (collected 2018-2020)
Land Use: 2019 NLCD
Hydrologic Method:
WV 2010 Regional Regression Equations
Additional Model Notes:
None
END DESCRIPTION:
DSS Export Rating Curves= 0
DSS Export Rating Curve Sorted= 0
DSS Export Volume Flow Curves= 0
DXF OffsetX= 0
DXF OffsetY= 0
DXF ScaleX= 0
DXF ScaleY= 0

--- BARKERRN.p01 (plan) ---

Plan Title=Floodplain
Program Version=4.00
Geom File=g01
Flow File=f01
K Sum by GR=0
Std Step Tol=0.01
Critical Tol=0.01
Num of Std Step Trials=20
Max Error Tol=0.3
Flow Tol Ratio=0.001
Split Flow NTrial=30
Split Flow Tol=0.02
Split Flow Ratio=0.02
Log Output Level=0
Friction Slope Method=1
Unsteady Friction Slope Method=2
Unsteady Bridges Friction Slope Method=1
Global Log Level=0
CheckData=False
Run HTab=0
Run UNet=0
Run PostProcess=0
UNET Theta=0
UNET Theta Warmup=0
UNET ZTol=0
UNET ZSATol=0
UNET MxIter=0
UNET MaxInSteps=0
UNET DtIC=0
UNET DtMin=0
UNET MaxCRTS=0
UNET WFStab=0
UNET SFStab=0
UNET WFX=0
UNET SFX=0
UNET DSS MLevel=0
UNET DZMax Abort=0
UNET Convert EG Bridges=0
UNET Use Existing IB Tables=0
UNET Froude Limit=0
UNET Froude Power=0
Write IC File=0
Echo Input=False
Echo Output=False
Write Detailed=0

--- BARKERRN.f01 (steady flow) ---

Flow Title=Flow
Program Version=6.31
Number of Profiles= 1
Profile Names=F01pct
River Rch & RM=BARKERRN,Main            ,6013
     913
Boundary for River Rch & Prof#=BARKERRN,Main            , 1
Up Type= 0
Dn Type= 3
Dn Slope=0.01054
DSS Import GetInterval= 0
DSS Import GetPeak= 0
DSS Import FillOption= 0

--- BARKERRN.g01 (geometry) ---

Geom Title=Geometry
Program Version=6.31

River Reach=BARKERRN        ,Main
Reach XY= 30
1641238.42710671400615.6531799641641289.43815231400354.005772174
     1641259.387      400223.461     1641157.087      400069.224
     1641151.185      399989.351     1641199.188      399900.429
     1641230.271      399765.472     1641458.872      399343.681
     1641582.813      399244.529     1641588.714       399094.62
     1641733.115      399017.108     1641911.746      398703.913
     1641935.747      398628.762     1641928.271      398560.693
     1641873.974      398361.208     1641796.855      398266.384
     1641891.963      397971.193     1641966.248      397846.041
     1642046.704       397611.27     1641982.176      397396.834
     1641872.825      397169.413     1641839.334      396923.893
     1641726.269      396605.347     1641682.704      396336.156
     1641578.957       396039.77     1641447.005      395873.572
     1641385.059      395706.618     1641209.292      395627.548
     1640983.749      395386.923      1640916.18      395361.054

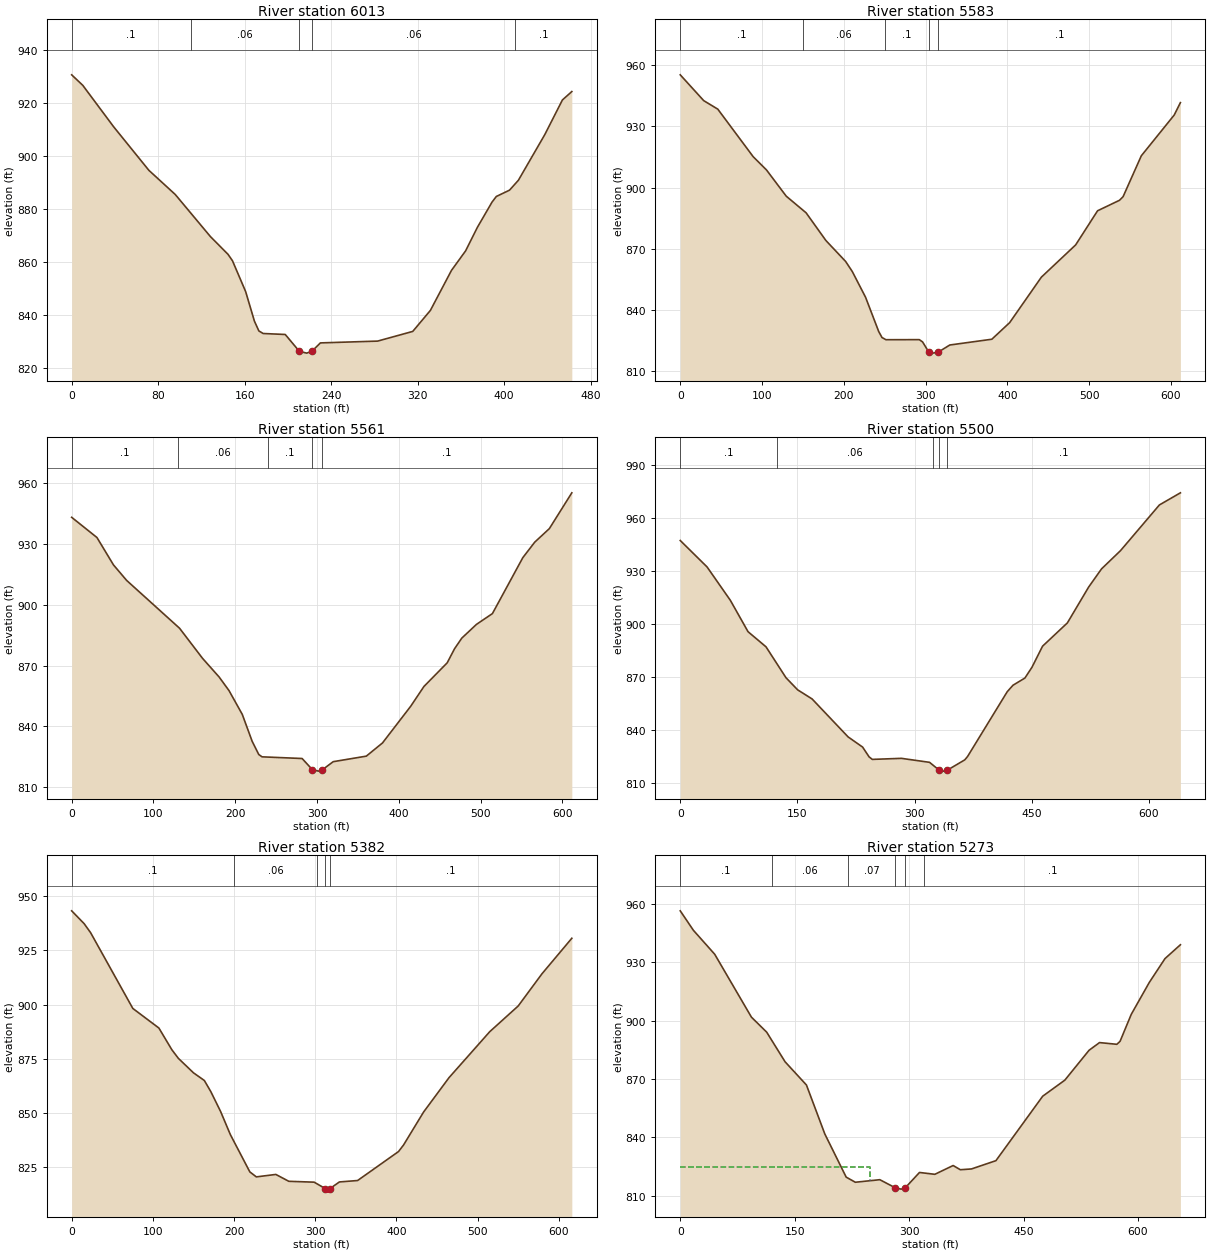
Type RM Length L Ch R = 1 ,6013    ,429.6,429.6,429.6
XS GIS Cut Line= 2
1641470.28232095400595.6564819651641015.47425756400511.432766522
#Sta/Elev= 30
       0  930.74    10.3  926.76    38.8  911.13    71.4  894.68    95.8  885.55
   128.3  869.66   144.6  862.95   148.7  860.53   160.9  848.87     169  837.72
   173.1  834.03   177.1  833.06   197.5  832.69   210.5  826.35   217.3  825.65
  222.11826.3345     230  829.51   282.9  830.19   315.4  833.85   331.7  841.77
   351.2  856.88   364.3  864.28   375.2  873.16   388.7  882.67   392.7  884.81
   404.9  887.19   413.1  890.93   437.5  908.16   453.8  921.25   462.5  924.42
#Mann= 5 ,-1,0
       0      .1       0     110     .06       0   210.5    .045       0
  222.11     .06       0     410      .1       0
Bank Sta=210.5,222.11
XS Rating Curve= 0 ,0
Exp/Cntr(USF)=0,0
Exp/Cntr=0.3,0.1

Type RM Length L Ch R = 1 ,5583    ,21.5,21.5,21.5
XS GIS Cut Line= 5
1641512.50015309400089.1017120491641247.19544944  400126.0548672
1641200.76712631400153.5328543631641168.55155515400197.118627105
1640957.25530903400301.345474967
#Sta/Elev= 30
       0  955.36    28.7  942.68    45.9  938.51    89.2  915.15   105.4  908.68
   129.6  895.77   153.9   887.6   178.1     874   202.3  863.68   210.4  858.75
   226.6  846.14   242.7  829.29   246.7  826.36   251.5  825.29   292.3  825.32
   296.3  824.22  303.85  819.26   308.6   818.7   315.7  819.25   329.6  822.69
     381  825.52   402.8  833.67   441.6  856.01   483.5  871.84   510.3   888.6
   537.1  893.75   541.5  895.52   563.8   915.6     604  935.61   611.6  941.71
#Mann= 5 ,-1,0
       0      .1       0     150     .06       0     250      .1       0
  303.85    .045       0   315.7      .1       0
Bank Sta=303.85,315.7
XS Rating Curve= 0 ,0
Exp/Cntr(USF)=0,0
Exp/Cntr=0.3,0.1

Type RM Length L Ch R = 1 ,5561    ,61,61,61
XS GIS Cut Line= 5
1641490.70726672400077.7315104641641225.40256307400114.684665615
1641178.97423993400142.1626527791641146.75866878400185.748425521
1640935.46242266400289.975273382
#Sta/Elev= 30
       0  942.98    30.9  933.04    51.1  919.56    67.2  911.92   131.9  888.37
   160.1   873.5   180.3  864.36   192.4  857.66   208.6  845.96   220.7   832.7
   228.8  826.18   232.8  825.04   281.8  824.21  294.46  818.67   301.9     818
   306.5  818.65   319.8  822.65   360.3  825.38   380.1  831.88   414.6  849.95
   430.8   859.7   459.2  871.33   468.2  878.27   477.1  883.51   494.9  890.23
   514.5  895.57   551.7  923.13   566.3  930.77   584.1   937.4   611.6  955.04
#Mann= 5 ,-1,0
       0      .1       0     130     .06       0     240      .1       0
  294.46    .045       0   306.5      .1       0
Bank Sta=294.46,306.5
XS Rating Curve= 0 ,0
Exp/Cntr(USF)=0,0
Exp/Cntr=0.3,0.1

Type RM Length L Ch R = 1 ,5500    ,118.3,118.3,118.3
XS GIS Cut Line= 6
1641486.04629217400005.8945120131641383.52320325400020.746516421
1641286.60082492400037.1372316781641207.16167934400058.634235919
1641118.47320843400104.8431330031640892.37129842 400225.43344301
#Sta/Elev= 30
       0   947.1    34.3  932.18    64.1  913.34    86.8  895.58   109.8  887.04
   135.4  869.57   150.3  862.74   168.8  857.59   214.9  836.15   233.5  830.39
   241.8  824.86   245.9  823.44   283.2  824.03   319.2  821.78   331.6  817.33
   337.2  816.81  341.81817.3201   364.3  823.18   367.9  825.08   418.6  861.63
     426  865.32   441.3   869.4   450.3  875.46   463.9  887.39   495.7  900.56
   522.9  920.79   539.4  931.07   563.7  941.37   613.5  967.19   640.4  974.04
#Mann= 5 ,-1,0
       0      .1       0  123.59     .06       0  324.19      .1       0
   331.6    .045       0  341.81      .1       0
Bank Sta=331.6,341.81
XS Rating Curve= 0 ,0
Exp/Cntr(USF)=0,0
Exp/Cntr=0.3,0.1

Type RM Length L Ch R = 1 ,5382    ,109.3,109.3,109.3
XS GIS Cut Line= 4
1641471.44109181399982.3481527241641199.39849093399988.875490671
1641114.75365691399945.7108365061640955.36027543400136.688111275
#Sta/Elev= 30
       0  943.29    15.3  937.39    23.3  933.22    75.3  898.25   107.4  889.21
   123.4  879.17   131.4  875.21     150  868.54   163.4  864.99   171.4  859.83
   183.4  850.69   195.4  840.04   219.4  822.82   227.4  820.52   251.4  821.65
   267.4  818.48   298.6  818.08   312.3815.1266   316.2  814.87  318.12  815.14
   329.7  818.18   352.1  818.84   402.5  832.21   408.7  835.24   433.3  850.41
   464.7  866.32   514.8  887.51   549.9  899.39   579.2  914.26   615.9  930.63
#Mann= 5 ,-1,0
       0      .1       0     200     .06       0  302.12      .1       0
   312.3    .045       0  318.12      .1       0
Bank Sta=312.3,318.12
XS Rating Curve= 0 ,0
Exp/Cntr(USF)=0,0
Exp/Cntr=0.3,0.1

Type RM Length L Ch R = 1 ,5273    ,39.9,39.9,39.9
XS GIS Cut Line= 3
1641489.28599152399885.8593587191641070.48356648399863.118955549
1640862.97738755399750.364456499
#Sta/Elev= 30
       0  956.48    17.2  946.48    45.2  934.13    93.3   901.8   113.3  894.08
   137.4  878.85   165.4  866.91   189.5  841.73   217.5  819.53   229.5   816.9
   261.6  818.21  282.12     814   289.6  813.36   294.8 813.988   313.6  821.93
   333.7  820.98   357.7   825.5   367.1  823.34   381.7  823.73   413.8     828
   475.1  861.15   504.1   869.4   535.9  884.78   549.6  888.72   572.3  887.84
   576.5  889.37   591.2  903.26   614.8  919.64   635.4  931.92   655.6  939.03
#Mann= 6 ,-1,0
       0      .1       0     120     .06       0     220     .07       0
  282.12    .045       0   294.8     .07       0     320      .1       0
#XS Ineff= 2 , 0
           249.1  824.85
Permanent Ineff=
       F       F
Bank Sta=282.12,294.8
XS Rating Curve= 0 ,0
Exp/Cntr(USF)=0,0
Exp/Cntr=0.3,0.1

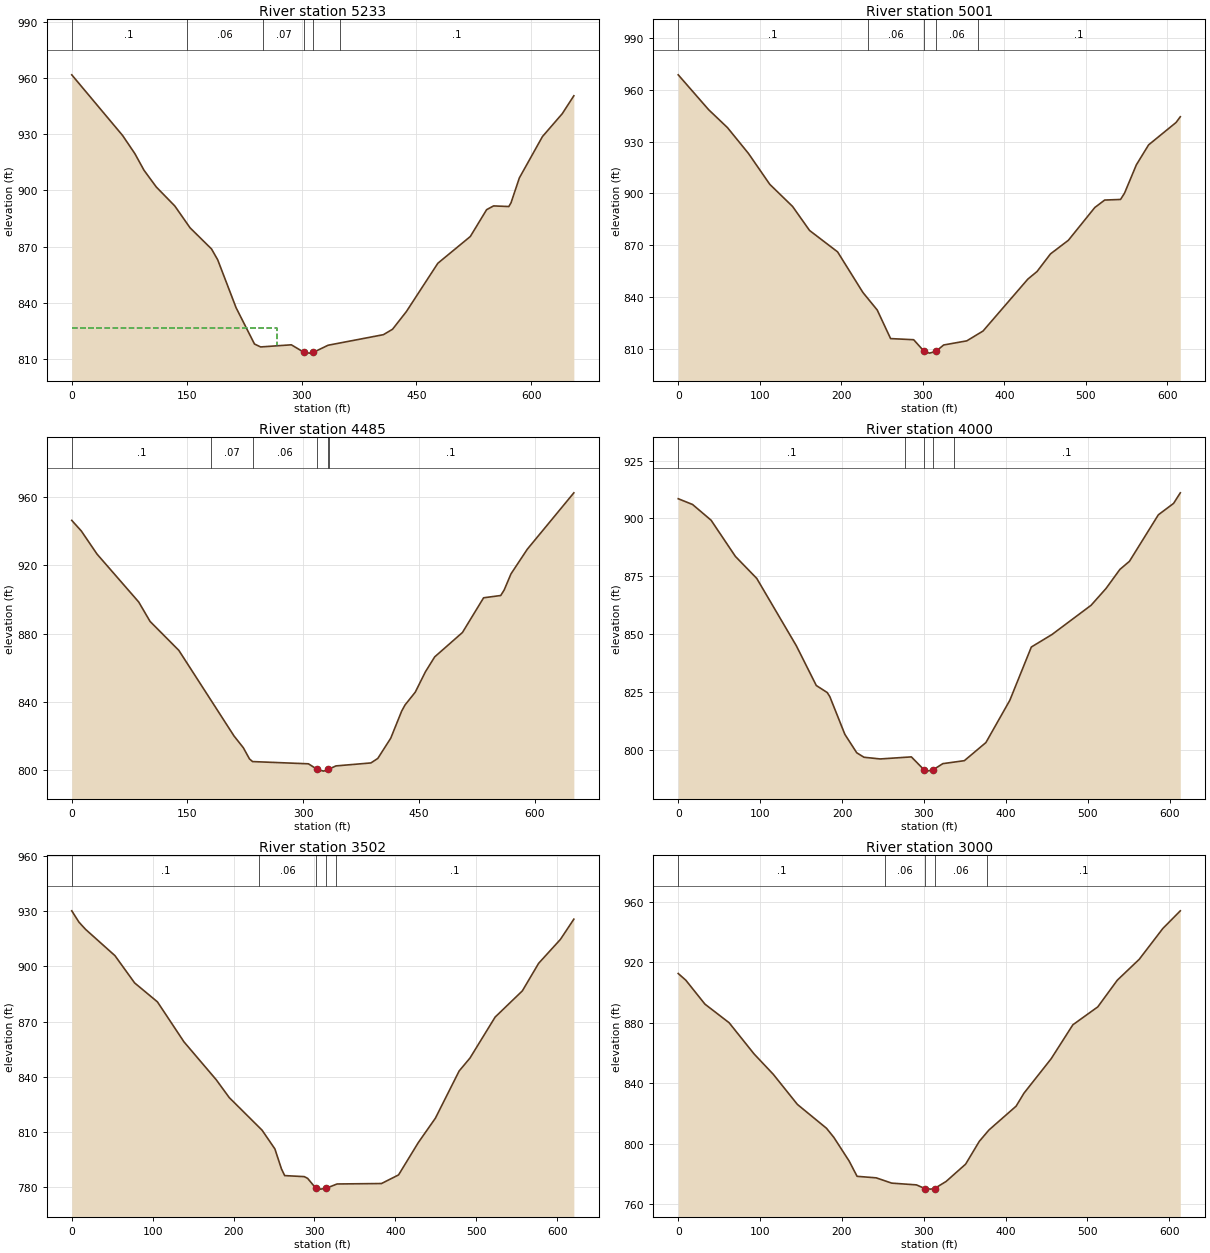
Type RM Length L Ch R = 1 ,5233    ,232.2,232.2,232.2
XS GIS Cut Line= 3
1641514.39518669 399847.484928371641095.59276165  399824.7445252
1640888.08658272 399711.99002615
#Sta/Elev= 30
       0  961.87    66.4   929.4    82.4   919.7    94.4  910.77   110.4  901.84
   134.5  891.72   154.5     880   182.5  868.69   190.6  862.86   214.6  837.23
   238.6  817.83   246.6  816.27   286.7  817.41  303.49  813.33   310.7  812.96
  315.17  813.33   334.8  817.19   406.9  822.83   418.9  825.75   436.9  835.18
     478  861.04   520.4  875.36   541.7  889.72   550.8  891.73   570.7   891.4
   573.6  893.42   584.4  906.67   614.6  928.83   640.4  941.04   655.6  950.66
#Mann= 6 ,-1,0
       0      .1       0     150     .06       0     250     .07       0
  303.49    .045       0  315.17     .07       0     350      .1       0
#XS Ineff= 2 , 0
          268.22  826.36
Permanent Ineff=
       F       F
Bank Sta=303.49,315.17
XS Rating Curve= 0 ,0
Exp/Cntr(USF)=0,0
Exp/Cntr=0.3,0.1

Type RM Length L Ch R = 1 ,5001    ,515.7,515.7,515.7
XS GIS Cut Line= 6
1641556.80435276399815.4201554211641477.61520667399764.111531004
1641405.87584884399713.3134042621641276.32459876399595.590214506
1641216.80437659399548.6785629241641067.81911026399442.794260249
#Sta/Elev= 30
       0  968.67    37.3  948.49    60.4  938.12    86.2  923.14   112.3  905.31
   140.3  892.48   161.1   878.6   195.5  866.21   226.5  842.75   244.1  832.58
   260.5  816.03   288.8  815.38  301.62808.6497   308.3  807.62   316.1808.6314
   325.6  812.33     354  814.73   373.9  820.41   428.9  850.47   440.1  854.82
   456.6  865.03   478.6  872.93     511  891.88   523.1   896.2   542.6  896.55
   547.5  900.23     562   916.6     577  928.13   610.7   941.1   615.9  944.41
#Mann= 5 ,-1,0
       0      .1       0  232.26     .06       0  301.62    .045       0
   316.1     .06       0  367.31      .1       0
Bank Sta=301.62,316.1
XS Rating Curve= 0 ,0
Exp/Cntr(USF)=0,0
Exp/Cntr=0.3,0.1

Type RM Length L Ch R = 1 ,4485    ,485.1,485.1,485.1
XS GIS Cut Line= 6
1641881.19215542 399296.19448784 1641791.8662186399250.058425263
1641703.46186784399216.681523502 1641625.6322991 399213.00830251
 1641525.1026445399212.748132423 1641274.8118065399093.033148751
#Sta/Elev= 30
       0  946.39    12.4  940.18    32.7  926.67    86.8  898.56   101.5  887.19
   138.8  870.22   210.4  820.01   222.4  813.16   230.4   806.6   234.4  805.04
   306.8  803.73   318.5  800.42   326.5  799.44  332.43800.4103   342.5   802.5
   387.8  804.24   396.7  806.86   413.5  818.72   427.6  834.53     432  838.19
   445.3  845.71   458.5  857.67   470.5   866.4   506.5   880.7   533.9  901.03
   556.1  902.37   560.5  905.53   569.4  915.04   590.5  929.46   650.9  962.55
#Mann= 6 ,-1,0
       0      .1       0  180.54     .07       0  235.03     .06       0
   318.5    .045       0  332.43     .06       0  332.95      .1       0
Bank Sta=318.5,332.43
XS Rating Curve= 0 ,0
Exp/Cntr(USF)=0,0
Exp/Cntr=0.3,0.1

Type RM Length L Ch R = 1 ,4000    ,498.4,498.4,498.4
XS GIS Cut Line= 6
1642091.07756242399005.4700036791642010.77555767398956.356256753
 1641936.1356151398910.2087112521641872.08259359398871.175980926
1641721.24365643 398782.44814001  1641565.017919398690.551342174
#Sta/Elev= 30
       0  908.52    17.5  906.03    40.1  899.25    69.8   883.6    95.9  874.08
   144.3  844.93   168.6  827.81   181.9  824.79   185.1  823.02   203.5   806.7
     218  798.74   226.8  796.82   246.6  796.08   284.7  796.97  300.34791.3285
   303.3  790.82  310.81791.3056   323.1  794.05   349.4  795.34   375.7  803.16
   404.9  821.41   431.2  844.45   456.4  849.85   504.2   862.5   522.4  869.74
   539.3  877.97     551  881.48   586.3  901.58   604.9  906.51   613.1  911.07
#Mann= 5 ,-1,0
       0      .1       0  276.89     .06       0  300.34    .045       0
  310.81     .06       0  336.89      .1       0
Bank Sta=300.34,310.81
XS Rating Curve= 0 ,0
Exp/Cntr(USF)=0,0
Exp/Cntr=0.3,0.1

Type RM Length L Ch R = 1 ,3502    ,501.6,501.6,501.6
XS GIS Cut Line= 6
1642180.96517792398340.5937087541642088.18682018398354.203261584
 1641926.9994785398374.8229710011641828.15879692398390.322283834
1641757.24456868 398419.782854841641589.35710917398503.445089087
#Sta/Elev= 30
       0  930.22     8.9  924.07      17  920.18    53.4  905.87    77.7  891.07
   105.9  880.78   138.7  859.07   178.6  838.48   194.7  828.79   235.3  811.08
   251.1  800.93   259.2  790.12   263.2  786.43   287.5  785.86   291.6  784.92
  301.77779.5598   307.8  779.08  314.51779.5573     328  781.88   382.9  782.12
     404   786.8   428.4  804.35   449.5  817.58   478.9  843.23   492.3  850.27
   523.4  872.52     557  886.73   577.2  901.73   604.1   914.7   620.7  925.69
#Mann= 5 ,-1,0
       0      .1       0  231.27     .06       0  301.77    .045       0
  314.51     .06       0  326.27      .1       0
Bank Sta=301.77,314.51
XS Rating Curve= 0 ,0
Exp/Cntr(USF)=0,0
Exp/Cntr=0.3,0.1

Type RM Length L Ch R = 1 ,3000    ,500,500,500
XS GIS Cut Line= 6
1642180.51931268398083.4390393351642094.81377542398043.637281671
1642018.81983292398000.0487861781641955.20709926397960.309364334
1641871.03043035397906.3252203321641655.32646543397767.992819846
#Sta/Elev= 30
       0  912.69     9.3  908.26    32.6  892.46    62.2  880.13    92.8  859.42
   116.1  846.05   145.6  826.11   181.1  810.36     190  804.41   208.9  788.58
   218.5  778.56   241.9  777.55   260.8  774.06     291   772.9  301.37770.4732
   308.3  770.09   313.1  770.47   327.3  775.18   351.1  786.61   367.8  801.68
   379.6   809.2   412.8  824.96   422.3  833.48   455.6  856.31   482.1  878.77
   512.6  890.64   536.4  908.27   563.2  922.09   592.1  942.51   613.4  954.16
#Mann= 5 ,-1,0
       0      .1       0   252.1     .06       0  301.37    .045       0
   313.1     .06       0  377.11      .1       0
Bank Sta=301.37,313.1
XS Rating Curve= 0 ,0
Exp/Cntr(USF)=0,0
Exp/Cntr=0.3,0.1

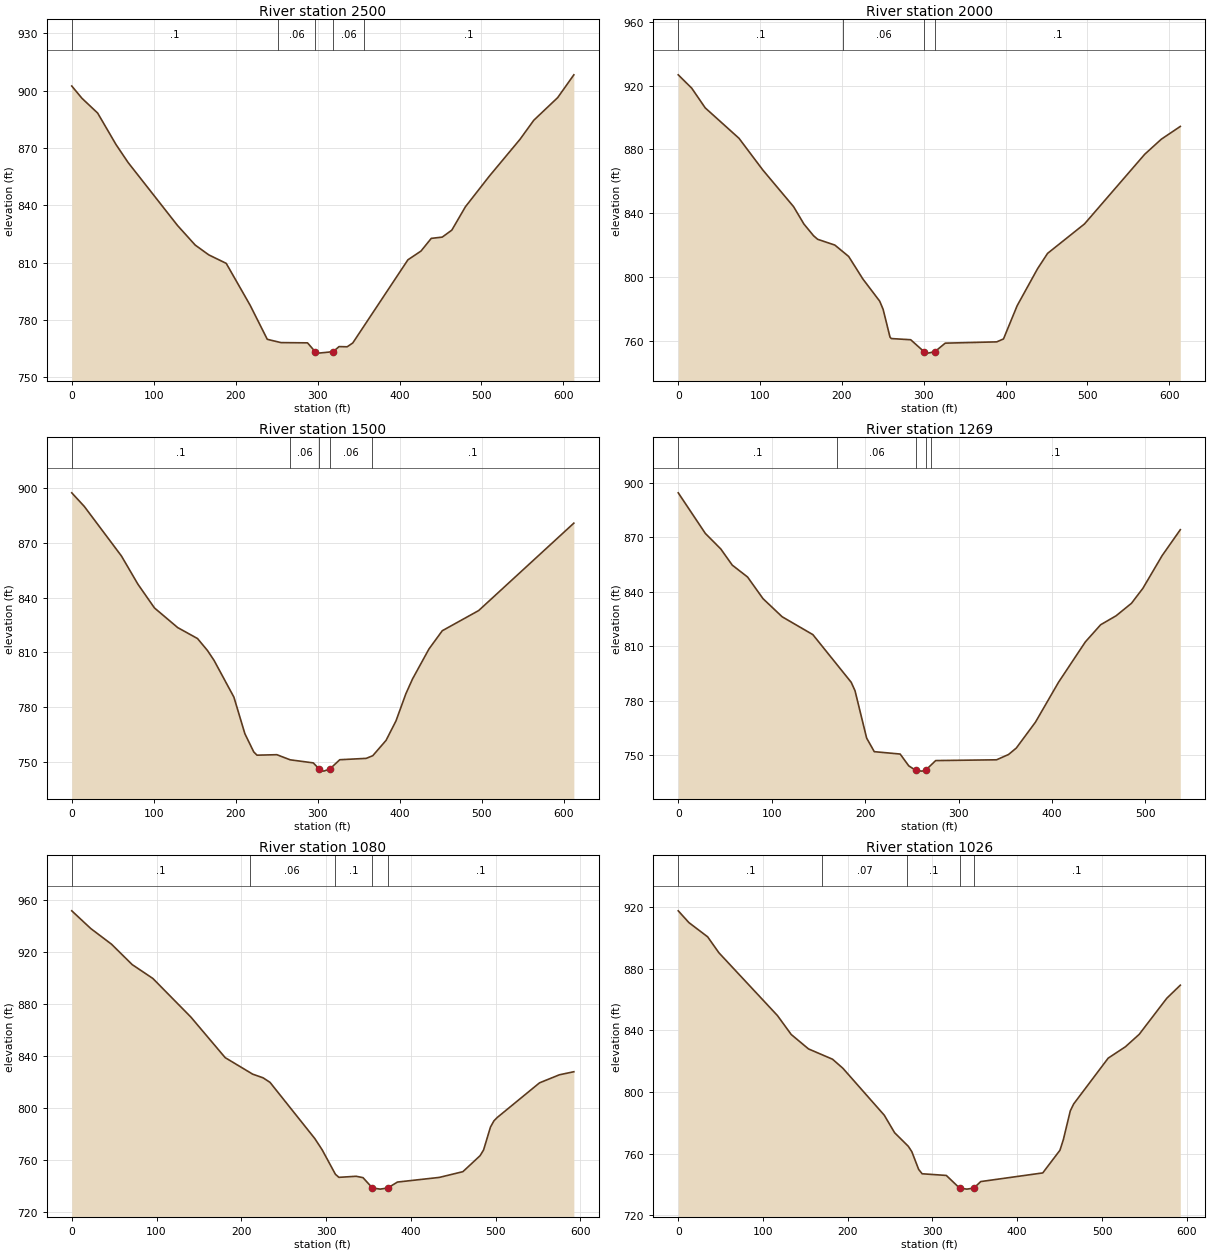
Type RM Length L Ch R = 1 ,2500    ,500,500,500
XS GIS Cut Line= 6
1642293.94657926 397374.506402091642205.44019459397405.846890584
1642122.59554401 397434.282529251642050.99627776397456.641408429
1641955.03944868397484.7889899161641709.14722392397556.920079261
#Sta/Elev= 30
       0  902.45    12.4  896.04    31.6  888.28      54   871.8    68.8  862.37
   129.1   829.4   150.6  819.18   167.2  814.03   188.5  809.58   217.6  787.71
   238.6  769.81   255.3  768.09   287.7  767.96     297  763.36   301.2  762.58
  318.89763.3383   326.2     766   336.1   765.9   342.9  767.89   410.2  811.44
   426.2  816.04   438.7  822.67   452.1  823.33   463.8  826.99   480.4  839.23
   509.6  855.27   547.1  874.59   563.8  884.51     593  896.39   612.7  908.31
#Mann= 5 ,-1,0
       0      .1       0  251.48     .06       0     297    .045       0
  318.89     .06       0  356.49      .1       0
Bank Sta=297,318.89
XS Rating Curve= 0 ,0
Exp/Cntr(USF)=0,0
Exp/Cntr=0.3,0.1

Type RM Length L Ch R = 1 ,2000    ,500,500,500
XS GIS Cut Line= 6
1642148.07482375 396912.697942511642057.09075376396935.902292416
1641807.55942868 397017.405410261641735.53266984397038.495919257
1641649.93933709397058.2130714211641557.37357734397076.322287172
#Sta/Elev= 30
       0  926.71    16.5  918.35      33  906.02    74.3  886.98   103.3  867.21
     141   844.2   153.6  833.36   165.4  826.01   170.4   823.8   191.4  820.19
   208.3  813.06   225.6  799.01   246.2   785.1   250.4  779.98   258.8  762.63
   260.4   761.7   284.1  760.95  300.34 753.507   305.2  752.58   313.7   753.5
   326.3  758.82   389.2  759.62   397.5  761.45   414.2  782.25   439.1  805.36
   451.4     815   496.5  833.41   570.1     877   590.4  886.44   613.6  894.42
#Mann= 4 ,-1,0
       0      .1       0  201.41     .06       0  300.34    .045       0
   313.7      .1       0
Bank Sta=300.34,313.7
XS Rating Curve= 0 ,0
Exp/Cntr(USF)=0,0
Exp/Cntr=0.3,0.1

Type RM Length L Ch R = 1 ,1500    ,231.4,231.4,231.4
XS GIS Cut Line= 6
1642020.15611634 396483.411071421641766.13661125396517.148208678
1641667.00721633396530.3138647531641592.66025217396540.188516915
1641505.92190859396551.7098193321641413.00608392396564.188468918
#Sta/Elev= 30
       0  897.58    15.3  890.11    60.6  862.92    80.7  847.45   100.9  834.42
   129.2  823.66   153.4  817.64   165.5   811.1   173.6  805.64   197.8  785.49
   211.2  765.41     222  755.45     226  753.65   250.2  753.91   266.4  751.11
   294.6  749.42  301.95746.0354   307.4   744.9   314.8  746.04   326.9  751.15
   359.2   751.9   367.2  753.36   383.4  761.76   395.5  772.43   407.6  787.36
   415.7  795.47   435.8  811.94     452  821.92   496.4  832.99   612.5  880.95
#Mann= 5 ,-1,0
       0      .1       0  266.25     .06       0  301.95    .045       0
   314.8     .06       0  366.25      .1       0
Bank Sta=301.95,314.8
XS Rating Curve= 0 ,0
Exp/Cntr(USF)=0,0
Exp/Cntr=0.3,0.1

Type RM Length L Ch R = 1 ,1269    ,188.5,188.5,188.5
XS GIS Cut Line= 2
1641920.39980172396239.5920715611641397.15996953396361.716458954
#Sta/Elev= 30
       0  894.49      29  872.12    45.5   863.6    57.8  854.67    74.2  848.12
    90.7  836.21   111.2  826.22   144.1  816.37   185.1  790.13   189.2  785.46
   201.6  759.42   209.8  751.91   237.5   750.6   246.7   744.1   254.1  741.64
   260.8  741.19  264.64  741.64   275.5     747   340.7  747.43   353.5  750.36
   361.8  753.91   382.3  768.18   406.9  790.08   435.7  812.39   452.1  821.84
   468.5  826.73     485  833.62   497.3  841.93   517.8  859.87   537.3  874.18
#Mann= 5 ,-1,0
       0      .1       0     170     .06       0   254.1    .045       0
  264.64     .06       0     270      .1       0
Bank Sta=254.1,264.64
XS Rating Curve= 0 ,0
Exp/Cntr(USF)=0,0
Exp/Cntr=0.3,0.1

Type RM Length L Ch R = 1 ,1080    ,54.4,54.4,54.4
XS GIS Cut Line= 2
1641962.26859396396059.5500265111641379.25374717396164.742307735
#Sta/Elev= 30
       0  951.76    22.5   938.1    46.9   926.1    71.3  910.42    95.7  899.75
   140.4  870.18     181  838.89   213.5  826.18   225.7  823.39   233.9  819.89
   286.7  776.73   295.4  768.08   311.1  749.19   315.2  746.86   335.5  747.68
   343.6  746.63  354.76  738.69   363.9   737.8  372.78  738.69   384.3  743.24
   433.6   746.8   461.5  751.22   481.8  763.53   485.9  767.93     494  785.45
   498.1  790.29   502.1  792.92   551.9  819.51   575.3  825.69   592.4  828.05
#Mann= 5 ,-1,0
       0      .1       0     210     .06       0     310      .1       0
  354.76    .045       0  372.78      .1       0
Bank Sta=354.76,372.78
XS Rating Curve= 0 ,0
Exp/Cntr(USF)=0,0
Exp/Cntr=0.3,0.1

Type RM Length L Ch R = 1 ,1026    ,175.7,175.7,175.7
XS GIS Cut Line= 2
1641923.34150684396011.5102370641641340.32666005396116.702518287
#Sta/Elev= 30
       0  917.65    12.6     910    34.7  900.76      48   890.4   117.1  849.59
   133.3  837.33   153.7  827.95   182.1  821.24   194.3  815.37   243.1  784.89
   255.3  773.51   271.5  764.68   275.6  761.21   283.7  749.66   287.8  746.84
   316.3  745.76  331.96  737.55   340.6  736.87   348.8  737.54   356.9  741.78
   430.1   747.4   450.4  762.14   454.4  769.03   462.6  787.71   466.6  792.22
   507.3  821.96   527.6  829.33   543.9  837.42   576.4  860.83   592.4  869.35
#Mann= 5 ,-1,0
       0      .1       0     170     .07       0     270      .1       0
  331.96    .045       0   348.8      .1       0
Bank Sta=331.96,348.8
XS Rating Curve= 0 ,0
Exp/Cntr(USF)=0,0
Exp/Cntr=0.3,0.1

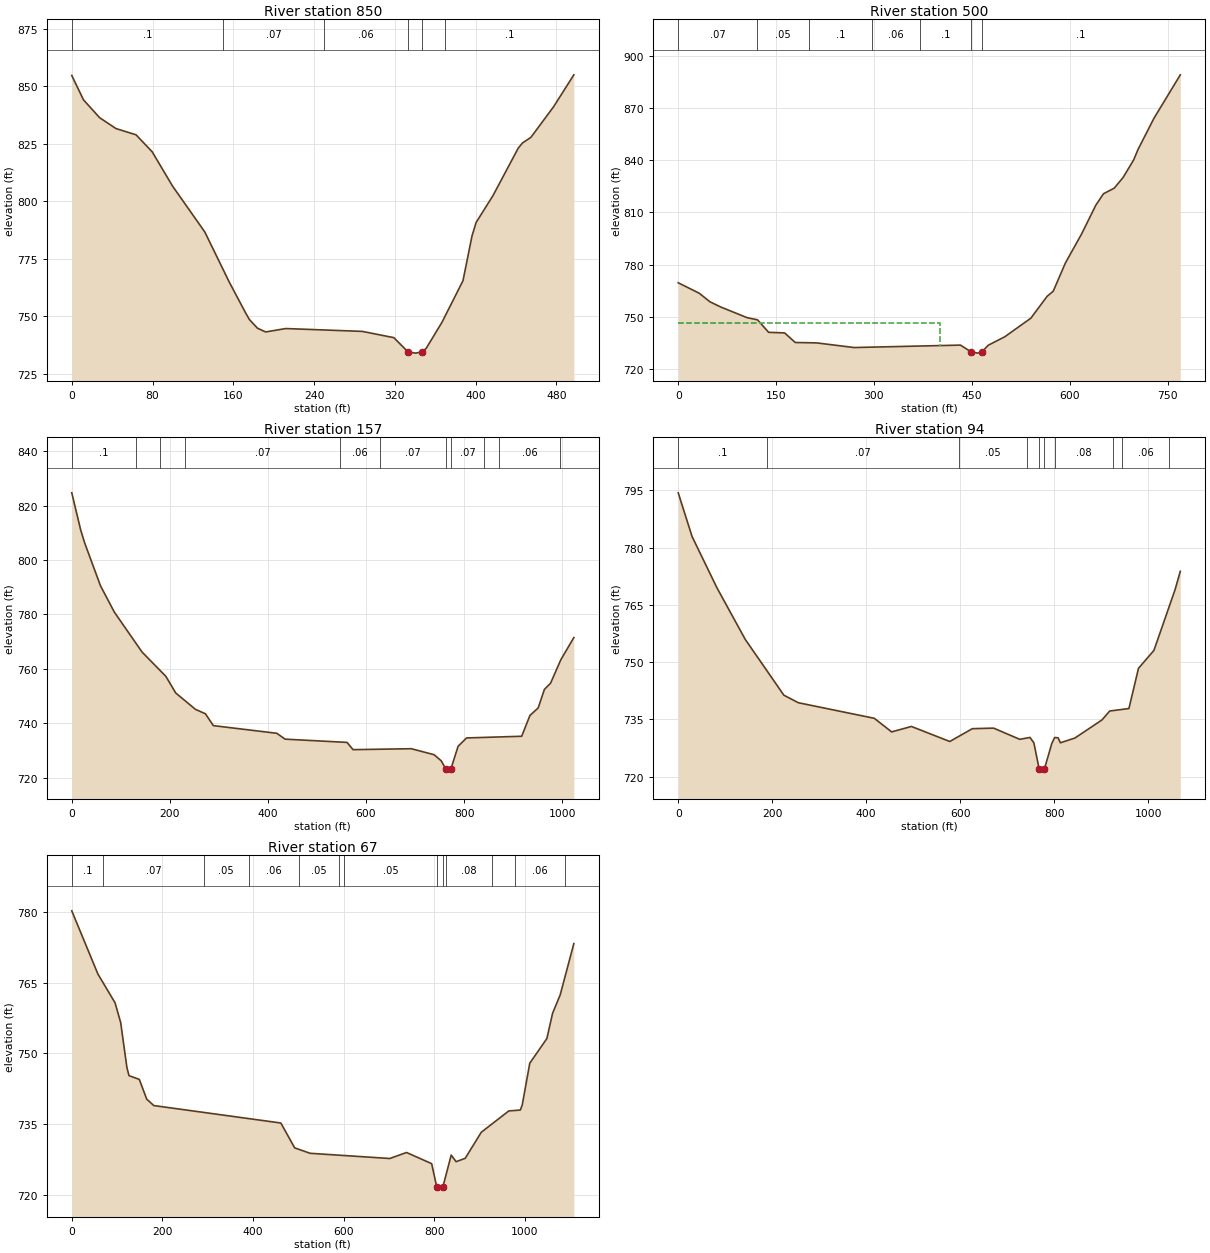
Type RM Length L Ch R = 1 ,850     ,350,350,350
XS GIS Cut Line= 4
1641807.71117978395872.4433669061641538.66319989395888.820200465
1641446.25106767395966.0252729551641343.31097102 395996.43939242
#Sta/Elev= 30
       0  854.76    11.6  844.14    27.6  836.37    43.7  831.65    63.7  828.91
    79.7  821.49    99.8  806.61   131.8   786.6   155.9  764.88   171.9  751.62
   175.9  748.52   183.9  744.73     192  743.09     212  744.57   287.8  743.33
     319  740.61  333.05  734.42   340.6  733.87  347.13  734.42   351.1  735.98
   366.7   747.3   387.5  765.41   396.4  784.82   400.5  790.75   417.2  802.44
   442.2  823.09   446.4  825.35   454.8  827.82   477.4  841.24   497.3  855.03
#Mann= 6 ,-1,0
       0      .1       0     150     .07       0     250     .06       0
  333.05    .045       0  347.13     .06       0  369.55      .1       0
Bank Sta=333.05,347.13
XS Rating Curve= 0 ,0
Exp/Cntr(USF)=0,0
Exp/Cntr=0.3,0.1

Type RM Length L Ch R = 1 ,500     ,343.4,343.4,343.4
XS GIS Cut Line= 6
1641655.65363702395460.0189711541641394.34068628395515.432580643
 1641340.6345095395548.5658282491641250.07596359395781.587671921
1641199.06130184395855.6370645021641133.43446459395930.410537004
#Sta/Elev= 30
       0  769.58    32.2  763.58    48.6  758.67      65  755.69   105.8  749.51
   121.5  748.32   138.6  741.12   163.1  740.78   179.4  735.28   212.2  735.05
   269.5  732.38   432.6  733.78448.5532729.9793   458.9  729.17465.6432729.9489
   475.2  733.71   500.6  738.58   540.5  749.24   565.5  761.84   574.8  764.74
   593.5  780.98   618.3  797.65   640.1  814.16   651.8  820.72   668.3  823.96
     682  830.13     698  840.11   704.9  846.27   729.2  864.09   769.6  889.06
#Mann= 7 ,-1,0
       0     .07       0     120     .05       0     200      .1       0
  297.12     .06       0  370.23      .1       0448.5532    .045       0
465.6432      .1       0
#XS Ineff= 2 , 0
          400.86  746.63
Permanent Ineff=
       F       F
Bank Sta=448.5532,465.6432
XS Rating Curve= 0 ,0
Exp/Cntr(USF)=0,0
Exp/Cntr=0.3,0.1

Type RM Length L Ch R = 1 ,157     ,63,63,63
XS GIS Cut Line= 5
1641790.14720991 395409.71068139 1641395.9237831395356.223080768
1641128.48577999395413.6727258811640920.47844424395494.894637936
1640880.85799934395617.718017143
#Sta/Elev= 30
       0   824.7    18.2  811.03    26.3  806.28    58.6  790.51    86.8  780.85
   143.3  766.17   191.8  757.24     212  751.11   252.3  745.08   272.5  743.47
   288.7  739.11   418.1  736.29     435  734.14   561.3  732.94   573.6  730.27
   692.4  730.62   738.7  728.42   753.4  726.16  763.13     723   769.6  722.38
   772.7  722.98   787.7   731.5   804.9  734.58   917.4   735.2   934.2  742.85
     951  745.61   963.7  752.42   976.3  754.72   997.3  763.371023.733  771.48
#Mann= 11 ,-1,0
       0      .1       0     130     .07       0     180      .1       0
     230     .07       0  547.84     .06       0  627.84     .07       0
  763.13    .045       0   772.7     .07       0  841.37     .08       0
  871.37     .06       0  994.68      .1       0
Bank Sta=763.13,772.7
XS Rating Curve= 0 ,0
Exp/Cntr(USF)=0,0
Exp/Cntr=0.3,0.1

Type RM Length L Ch R = 1 ,94      ,27,27,27
XS GIS Cut Line= 5
1641753.49829837395360.1851252591641359.27487157395306.697524636
1641091.83686846395364.147169749 1640883.8295327395445.369081805
1640847.36747713395615.568300948
#Sta/Elev= 30
       0  794.35    29.4  782.92    82.1  769.55   142.7  755.96   224.8  741.36
   255.7  739.38   417.4   735.3   454.3  731.74   496.3  733.17     578  729.23
   626.1  732.59   671.4  732.73   726.9   729.8   748.7  730.29     757  728.88
   768.2  722.05   771.4  721.47   779.5  722.05     795  728.65   801.2  730.27
   808.5   730.2   813.5  728.89   844.4  730.14     902  734.88   918.4  737.21
   959.3  737.86   979.7   748.4  1012.5  753.07  1057.5  768.97  1068.7   773.8
#Mann= 10 ,-1,0
       0      .1       0     190     .07       0  597.84     .05       0
  741.37     .07       0   768.2    .045       0   779.5     .07       0
  801.37     .08       0  924.68     .07       0  944.68     .06       0
 1044.68      .1       0
Bank Sta=768.2,779.5
XS Rating Curve= 0 ,0
Exp/Cntr(USF)=0,0
Exp/Cntr=0.3,0.1

Type RM Length L Ch R = 1 ,67      ,,,
XS GIS Cut Line= 5
1641722.79245357395318.5836581081641502.89898435395197.741301147
1641102.73249081395310.659569127 1640867.5773728395447.249749425
1640817.04314353395609.380401654
#Sta/Elev= 30
       0  780.18    57.8  766.79    95.6  760.72     108  756.54   121.7  747.06
   126.3  745.31   149.1  744.52   165.5  740.34   181.1  738.98   461.6  735.29
   492.1  730.03   526.3  728.88   702.1  727.78   739.1  729.05   794.6  726.69
  805.83  721.72   810.4   721.3   819.2  721.71   837.7   728.5   848.5  727.11
   868.6  727.81   904.1  733.33   964.8  737.84   990.3  738.03   994.5   739.1
  1011.2  747.95  1048.9  753.15  1061.5  758.49  1078.3  762.391108.473  773.25
#Mann= 13 ,-1,0
       0      .1       0      70     .07       0  290.91     .05       0
  390.91     .06       0  500.91     .05       0  590.91     .07       0
  600.91     .05       0  805.83    .045       0   819.2      .1       0
   826.7     .08       0   926.7     .07       0  978.65     .06       0
 1088.65      .1       0
Bank Sta=805.83,819.2
XS Rating Curve= 0 ,0
Exp/Cntr(USF)=0,0
Exp/Cntr=0.3,0.1
LCMann Table=0

Chan Stop Cuts=-1
Use User Specified Reach Order=0
Composite Channel Slope=5